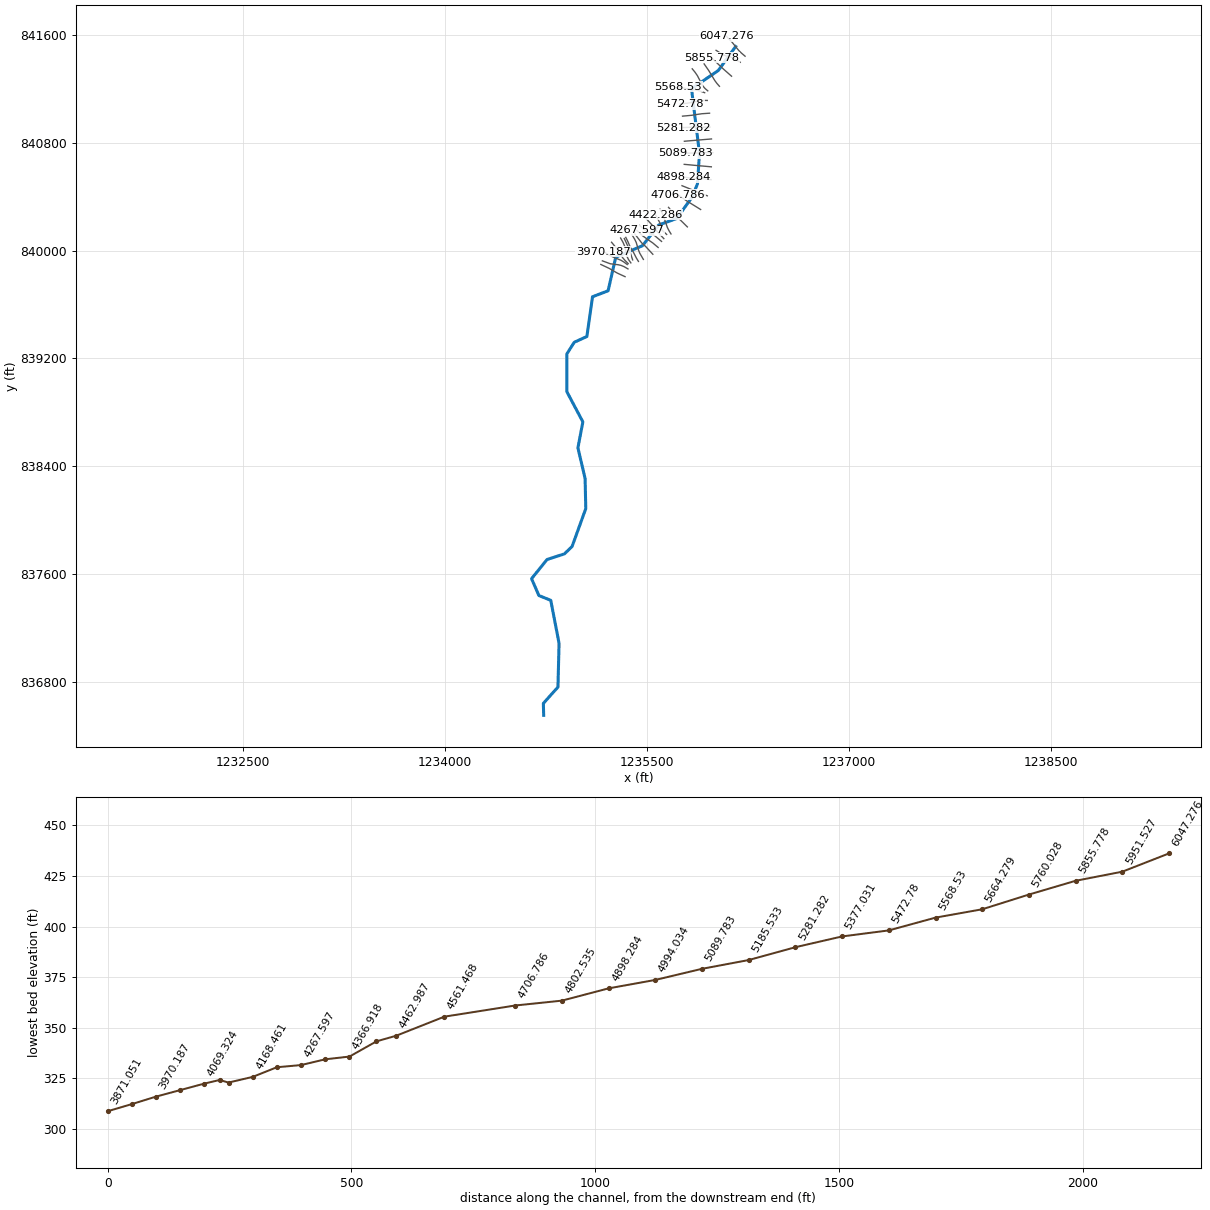
--- 21_ras.prj (project) ---

Proj Title=21
Current Plan=p01
Default Exp/Contr=0.3,0.1
English Units
Geom File=g01
Flow File=f01
Plan File=p01
Y Axis Title=Elevation
X Axis Title(PF)=Main Channel Distance
X Axis Title(XS)=Station
BEGIN DESCRIPTION:
RFD model 21 exported to HEC-RAS
END DESCRIPTION:

--- 21_ras.p01 (plan) ---

Plan Title=Plan 01
Program Version=4.10
Short Identifier=Plan 01
Geom File=g01
Flow File=f01
Subcritical Flow
Calc Critical at every XS
Secant Critical Depth

--- 21_ras.f01 (steady flow) ---

Flow Title=Flow 01
Program Version=5.01
Number of Profiles= 5
Profile Names=10yr,25yr,50yr,100yr,500yr
River Rch & RM=21,48,6047.276
  576.62 1060.79 1558.57 2187.78 4259.82
River Rch & RM=21,48,5951.527
  580.79 1068.61  1570.3 2204.61 4294.46
River Rch & RM=21,48,5855.778
  583.76  1074.2 1578.68 2216.63 4319.22
River Rch & RM=21,48,5760.028
  588.51 1083.14 1592.09 2235.87 4358.86
River Rch & RM=21,48,5664.279
  592.08 1089.85 1602.15 2250.31 4388.61
River Rch & RM=21,48, 5472.78
  595.05 1095.44 1610.54 2262.34 4413.42
River Rch & RM=21,48,5377.031
  634.81 1170.29 1722.93 2423.76 4746.94
River Rch & RM=21,48,5281.282
  638.36 1176.99    1733 2438.24 4776.91
River Rch & RM=21,48,5185.533
   643.7 1187.04  1748.1 2459.95  4821.9
Boundary for River Rch & Prof#=21,48,1
Up Type= 0
Dn Type= 2
Boundary for River Rch & Prof#=21,48,2
Up Type= 0
Dn Type= 2
Boundary for River Rch & Prof#=21,48,2
Up Type= 0
Dn Type= 2
Boundary for River Rch & Prof#=21,48,2
Up Type= 0
Dn Type= 2
Boundary for River Rch & Prof#=21,48,2
Up Type= 0
Dn Type= 2

--- 21_ras.g01 (geometry) ---

Geom Title=21
Program Version=4.10

River Reach=21,48
Reach XY= 30
1236159.73252565841516.1561920551236031.07714581841338.067407801
1235831.91053366841202.2341203991235891.07716893840723.067593597
1235876.07716668 840495.567661241235836.07717555840397.234358126
1235721.91053778840238.9010749231235587.36749652840190.229700237
1235468.57727294840037.2344752331235269.41066228839952.234506168
1235212.74400495839702.2345816711235096.91070433839658.067931437
1235055.24404128839363.068019836  1234961.077401839319.734702067
1234906.07741461839233.0680626071234906.91073949838952.234812214
1235025.24403154838728.9015414291234988.57737001838536.401599375
  1235041.910681838308.068331942  1235046.910673838084.735064447
1234945.24402798837803.9018170641234888.57737635837748.901834972
 1234759.4107464837707.235184391  1234644.410776837564.735229862
1234698.57742311837439.7352652121234786.91072945837403.901939888
1234848.57736866837084.7353657161234840.24402828836759.735462004
1234731.91072322836638.9021675311234734.30647495836550.398095103

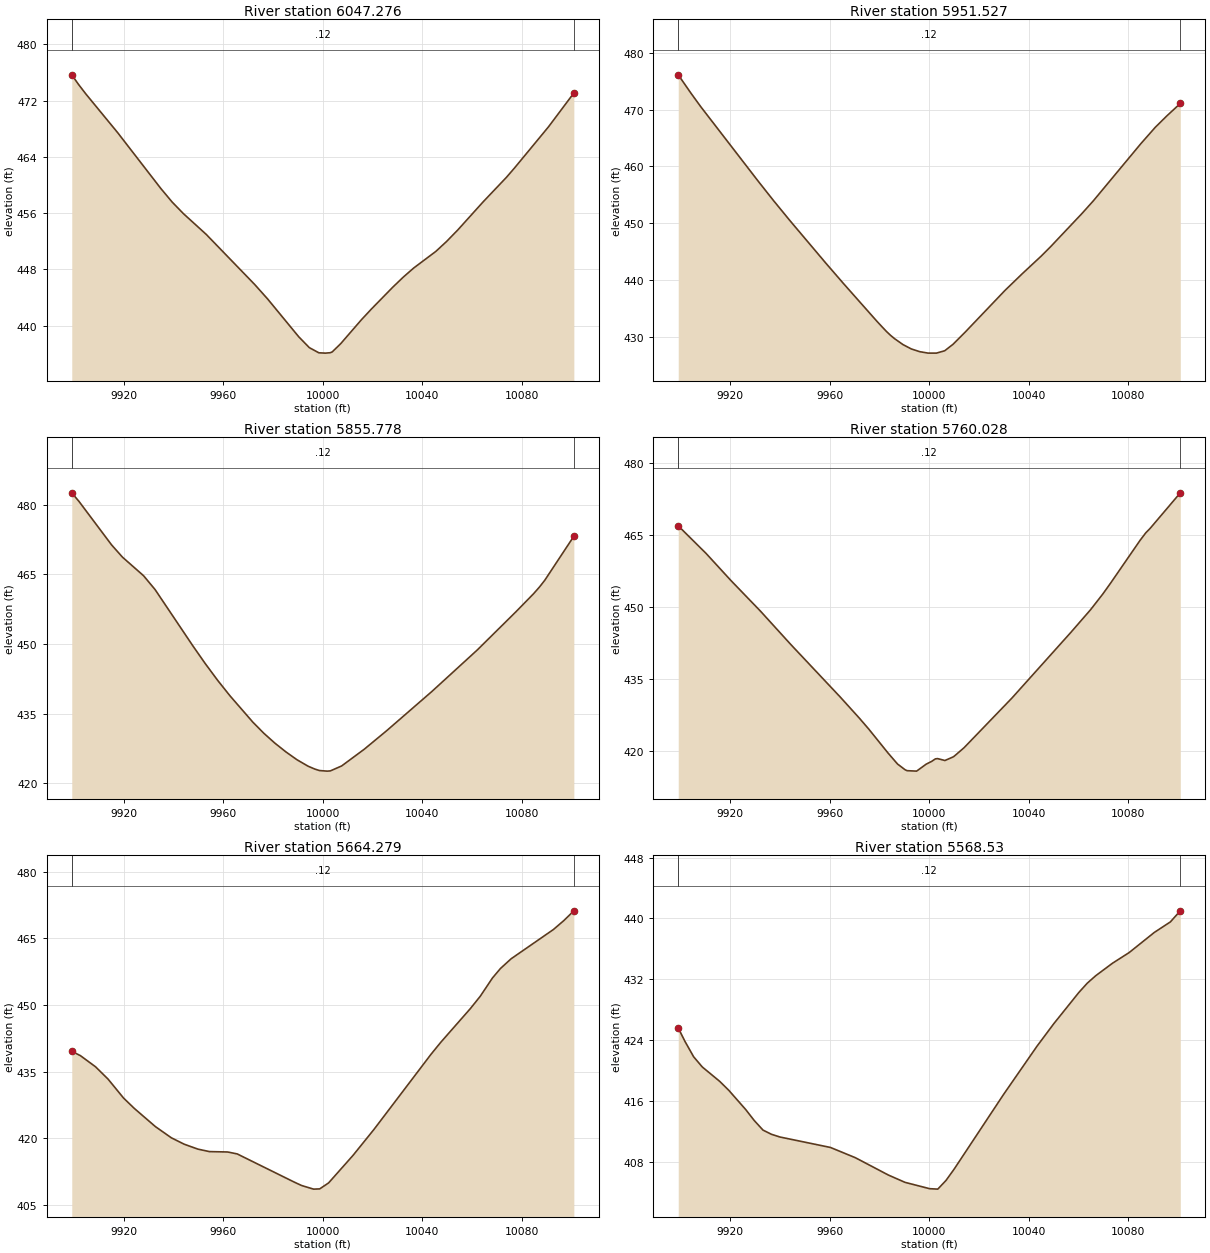
Type RM Length L Ch R = 1 ,6047.276,95.749300,95.749300,95.749300
XS GIS Cut Line= 6
1236229.72008669841444.0029721811236203.29813262841466.539812137
1236182.92380665841486.351721943 1236159.5069312841514.760087781
1236133.10205942841548.0655887961236091.83522064841590.878338347
#Sta/Elev= 30
9899.038475.65819901.712474.31549904.578472.99319917.515467.43389934.825459.5219
9939.401457.58389943.977455.9218 9953.13452.98059972.611445.86619977.769443.8268
9990.335438.43329994.587436.89289998.401436.1616   10001436.113710002.96436.1688
10003.78436.282810007.16437.442410015.54440.857210019.57442.387110028.13445.4766
10032.32 446.89710036.52448.194410045.46450.565110049.76451.970910054.31453.6202
10064.37457.563610073.82461.0778 10077.1462.416110090.77 468.26510100.97473.0743
#Mann= 3 , 0 , 0
9899.038    0.12       09899.038    0.12       010100.97    0.12       0
#XS Ineff= 2 , 0
       0                               0
Bank Sta=9899.038,10100.97
Exp/Cntr=0.3,0.1

Type RM Length L Ch R = 1 ,5951.527,95.749400,95.749400,95.749400
XS GIS Cut Line= 6
1236193.80123165 841398.982805241236136.52923175841432.633471433
1236117.23869696841439.7527729511236087.43109244841446.220062319
1236064.40888298841455.6489487431236014.34304618841487.591363339
#Sta/Elev= 30
9899.048476.11649904.242472.83329908.127470.48889931.203457.37799937.326 453.983
9944.072450.37649958.354442.96559965.535439.32829979.105432.61749982.602 430.978
9984.433430.21639986.097429.61539989.451428.58359992.804427.81799996.156427.3435
9999.503427.090310002.85427.086410006.22427.506110009.58428.655410014.48430.8085
10030.49438.156710037.58441.154610044.86444.120210048.63445.767510061.43451.7004
10066.05453.958210085.08463.992710090.83466.849310095.49468.866310100.94471.0724
#Mann= 3 , 0 , 0
9899.048    0.12       09899.048    0.12       010100.94    0.12       0
#XS Ineff= 2 , 0
       0                               0
Bank Sta=9899.048,10100.94
Exp/Cntr=0.3,0.1

Type RM Length L Ch R = 1 ,5855.778,95.749300,95.749300,95.749300
XS GIS Cut Line= 5
1236129.24930124 841295.377670551236069.75870086841347.849527304
1236054.62525505841361.9230956941236053.10137645841363.218392582
1235980.81355696841432.315575421
#Sta/Elev= 30
9899.009482.59279901.902480.75169915.026471.36849919.401468.72749927.925464.7056
9932.525 461.7379947.764449.57289952.724445.76789957.684442.17979962.644438.8406
9971.897433.13129976.271430.76099980.702428.63569985.182426.73039989.662425.0305
9994.143423.63769996.817423.03349998.623422.721210001.72422.592910003.05 422.643
10007.59423.711110016.66427.305410025.74431.3287 10043.9439.771610062.05448.6623
10077.69456.941510084.74 460.80710087.19462.293410089.28463.7202   10101 473.229
#Mann= 3 , 0 , 0
9899.009    0.12       09899.009    0.12       0   10101    0.12       0
#XS Ineff= 2 , 0
       0                               0
Bank Sta=9899.009,10101
Exp/Cntr=0.3,0.1

Type RM Length L Ch R = 1 ,5760.028,95.749300,95.749300,95.749300
XS GIS Cut Line= 6
1236039.33910132841220.4338996611236020.42117453841242.077477077
1236004.41162926 841263.820634351235980.66771044841303.424204406
1235959.61879564841337.7201144541235925.61074142 841386.80444769
#Sta/Elev= 30
9899.061466.85819910.311461.08549920.282455.45719932.191 449.0659944.414442.1045
9964.206431.21569971.882426.8282 9975.72424.51729983.397419.57789987.235417.2755
9990.282416.07689991.073415.88769994.911415.79199998.749417.2375   10001417.8326
10002.45418.336810003.34418.3999 10006.3418.005810009.62418.751110010.15418.9488
   10014420.665210033.25431.0061 10056.9444.653510064.88449.4041 10069.8452.6731
10072.87 454.89710084.84 463.88710087.08465.407710088.83466.333210100.95473.7288
#Mann= 3 , 0 , 0
9899.061    0.12       09899.061    0.12       010100.95    0.12       0
#XS Ineff= 2 , 0
       0                               0
Bank Sta=9899.061,10100.95
Exp/Cntr=0.3,0.1

Type RM Length L Ch R = 1 ,5664.279,95.749300,95.749300,95.749300
XS GIS Cut Line= 6
1235952.55896832841186.8473746341235931.26110646841205.299921625
1235913.89768525841226.2143568651235875.69658427841299.312784994
1235857.64532394841325.697315168 1235837.2700887841350.355246244
#Sta/Elev= 30
9899.079439.57749902.578438.59189908.649 436.087 9913.66433.32419919.942429.0245
9924.282426.68419932.741422.60089939.146420.08179944.282418.64969949.798417.5405
9954.441416.98239961.764416.89499965.595416.46059988.568410.10089991.528409.3363
9996.305408.52719998.773408.576910002.36409.930110012.17 416.12610020.64422.0077
 10043.5438.880810047.47441.6159 10059.4449.226510063.37452.004510068.26456.1093
10071.49458.248910075.74460.420810092.77467.024410097.02469.071510100.97 471.229
#Mann= 3 , 0 , 0
9899.079    0.12       09899.079    0.12       010100.97    0.12       0
#XS Ineff= 2 , 0
       0                               0
Bank Sta=9899.079,10100.97
Exp/Cntr=0.3,0.1

Type RM Length L Ch R = 1 , 5568.53,95.749300,95.749300,95.749300
XS GIS Cut Line= 6
1235929.49845613841173.0959309851235896.83089245841184.862981379
1235872.91457176841191.1726181351235843.53637568841196.453222102
1235799.52041691841201.3908254141235733.03657273841216.997843859
#Sta/Elev= 30
9899.032425.59269901.742423.82179905.229421.79949908.717420.45689915.691418.5739
9919.378417.38719926.152414.8675 9929.64413.40419933.127 412.1589936.537411.6062
 9939.93411.25169960.257409.87619970.257408.53069983.591406.24179990.234405.2892
10000.11404.457110003.41404.398210006.71405.538110010.02407.044410029.87416.8499
 10043.3423.187510050.04426.141410060.15430.260110063.52431.474910066.89432.4493
10073.63434.092710080.37435.502210090.48438.148210096.93439.530810100.94440.9911
#Mann= 3 , 0 , 0
9899.032    0.12       09899.032    0.12       010100.94    0.12       0
#XS Ineff= 2 , 0
       0                               0
Bank Sta=9899.032,10100.94
Exp/Cntr=0.3,0.1

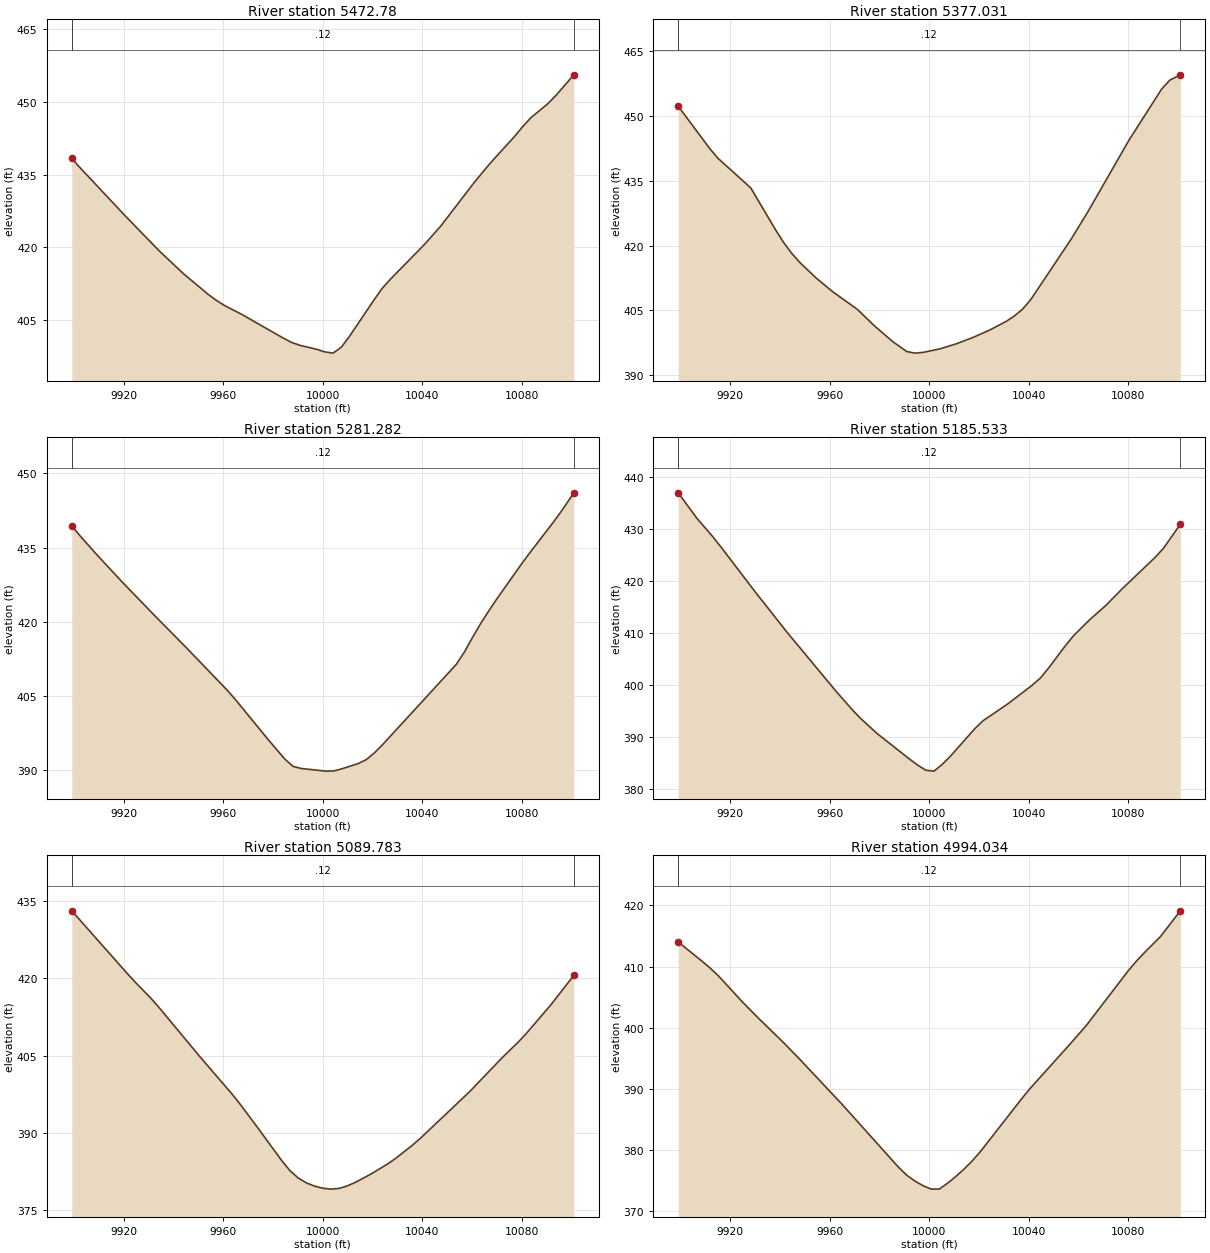
Type RM Length L Ch R = 1 , 5472.78,95.749300,95.749300,95.749300
XS GIS Cut Line= 6
1235948.94958624841115.488692439 1235927.9344265841115.820987518
 1235902.9927131841113.789656527 1235849.9593409841104.017741779
1235800.14635595841094.9633976761235749.08780216 841089.58168355
#Sta/Elev= 30
9899.032438.43059901.348436.9762 9920.05426.72279934.205419.2238 9944.08414.4475
9954.075410.16139957.411408.91639960.747407.85189967.419 406.097  9984.1401.1992
9987.436400.30839990.772399.70919997.444398.891210000.77398.3562 10004.1398.0915
10007.44399.306110010.77401.594910020.78409.227210024.11411.618610027.45413.5053
10040.79420.497410047.47424.363710060.68433.217610067.28437.318110077.18442.9073
10080.48444.943410083.78446.786410090.38449.573610093.67451.296810100.97455.6072
#Mann= 3 , 0 , 0
9899.032    0.12       09899.032    0.12       010100.97    0.12       0
#XS Ineff= 2 , 0
       0                               0
Bank Sta=9899.032,10100.97
Exp/Cntr=0.3,0.1

Type RM Length L Ch R = 1 ,5377.031,95.749300,95.749300,95.749300
XS GIS Cut Line= 6
1235965.89463657841020.7916063821235910.47601104841016.944901236
1235866.48819123841010.7651317381235864.57806294841010.172333364
1235832.42328015841005.166891403 1235765.2754387840998.922191296
#Sta/Elev= 30
9899.028452.22949911.758442.39989915.047440.16639928.202433.34449938.068423.7468
9941.356 420.7639944.645418.22539947.934416.08689954.511412.48639961.137409.3261
9971.076405.24439977.702401.5535 9985.32397.77079990.954395.48149994.267395.1117
9997.581395.286810004.28396.091810010.93397.279410017.57398.733110024.21400.4218
10030.85402.422410034.16403.668210037.46405.239810040.75407.433210057.23421.6216
10063.82427.830310080.29444.337410093.47456.204710096.77458.280410100.98459.4998
#Mann= 3 , 0 , 0
9899.028    0.12       09899.028    0.12       010100.98    0.12       0
#XS Ineff= 2 , 0
       0                               0
Bank Sta=9899.028,10100.98
Exp/Cntr=0.3,0.1

Type RM Length L Ch R = 1 ,5281.282,95.749300,95.749300,95.749300
XS GIS Cut Line= 6
1235970.00456836840917.4617210721235890.82090692840915.745627484
1235870.03326636840916.1670157631235868.03716121840916.291772394
1235840.36676989840916.6636287541235768.09368898840914.114102551
#Sta/Elev= 30
9899.006439.35639902.692437.17269909.256433.4639  9919.1428.13849932.227421.3084
9945.353414.62579961.761406.04229965.043404.14839978.208396.05589984.732392.2211
9988.014390.75919991.295390.330210001.14389.795110004.42389.831410007.71390.2681
10014.27391.331510017.55392.145410020.83393.520610024.11395.181610053.65411.3544
10056.94413.856810060.22416.8173 10063.5419.629710066.79422.204610070.07 424.656
10079.92431.6675 10083.2 433.88910093.05440.324410096.33442.606810100.99 446.067
#Mann= 3 , 0 , 0
9899.006    0.12       09899.006    0.12       010100.99    0.12       0
#XS Ineff= 2 , 0
       0                               0
Bank Sta=9899.006,10100.99
Exp/Cntr=0.3,0.1

Type RM Length L Ch R = 1 ,5185.533,95.749300,95.749300,95.749300
XS GIS Cut Line= 4
1235980.26797569840829.6246557821235880.62636921 840821.36569911
1235878.64119643840821.1226167871235779.02741243840812.522439066
#Sta/Elev= 30
9899.017436.9293 9906.43432.09419913.014428.44689916.306426.45979929.474 418.207
9942.642410.22739962.395398.86139968.979 395.2769972.271393.63699978.855390.7412
9992.024385.78969995.316384.62789998.608383.630310001.91383.4578 10005.2384.7504
10008.49386.318910018.37391.642110021.67393.151410031.55396.366610041.42399.9751
10044.72401.355310048.01403.2661 10054.6407.459110057.89409.399810064.48412.5315
10071.06415.310510077.65418.513110090.82424.513310094.11426.216510100.98430.8763
#Mann= 3 , 0 , 0
9899.017    0.12       09899.017    0.12       010100.98    0.12       0
#XS Ineff= 2 , 0
       0                               0
Bank Sta=9899.017,10100.98
Exp/Cntr=0.3,0.1

Type RM Length L Ch R = 1 ,5089.783,95.749400,95.749400,95.749400
XS GIS Cut Line= 6
1235991.72009338840727.9443513851235925.21257191840727.900431513
1235891.77123208840726.252112199 1235889.7806828840726.057912328
1235852.98111279840724.4592029011235789.82810976 840724.87302454
#Sta/Elev= 30
9899.011433.10599921.131421.05949924.412419.33629930.973416.08189934.254414.2787
9950.658 404.7569963.782 397.4039967.065395.38849973.634391.15659983.489384.6491
9986.773382.71589990.058 381.2929993.343380.35129996.628379.71019999.916379.3075
 10003.2379.122810006.49379.252510009.77379.733310013.06380.423910019.62382.1116
10026.19384.041310029.48385.151810036.04387.636110039.33389.016410059.01398.0089
10072.13404.6015 10078.7407.680410081.98409.380910091.82414.916810100.99420.5931
#Mann= 3 , 0 , 0
9899.011    0.12       09899.011    0.12       010100.99    0.12       0
#XS Ineff= 2 , 0
       0                               0
Bank Sta=9899.011,10100.99
Exp/Cntr=0.3,0.1

Type RM Length L Ch R = 1 ,4994.034,95.749300,95.749300,95.749300
XS GIS Cut Line= 4
1235979.11818396840622.6642395191235879.51607032840631.573415756
1235877.52599595840631.7724232531235777.96075604840641.072619419
#Sta/Elev= 29
    9899414.01479908.557410.89029911.851409.75439915.145408.49429925.026404.1332
9931.614401.42959941.496397.52619948.084394.77069964.554387.65139987.611377.2181
9990.905375.91839994.199374.95869997.493374.197210000.79373.632310004.08373.6495
10007.38 374.60310010.67 375.68810013.97376.895410017.26378.236110020.56 379.763
10037.04388.326910040.33389.972510056.81397.4119 10063.4400.488710079.87409.2233
10083.17410.820610086.46412.236910093.05 414.921   10101419.1118
#Mann= 3 , 0 , 0
    9899    0.12       0    9899    0.12       0   10101    0.12       0
#XS Ineff= 2 , 0
       0                               0
Bank Sta=9899,10101
Exp/Cntr=0.3,0.1

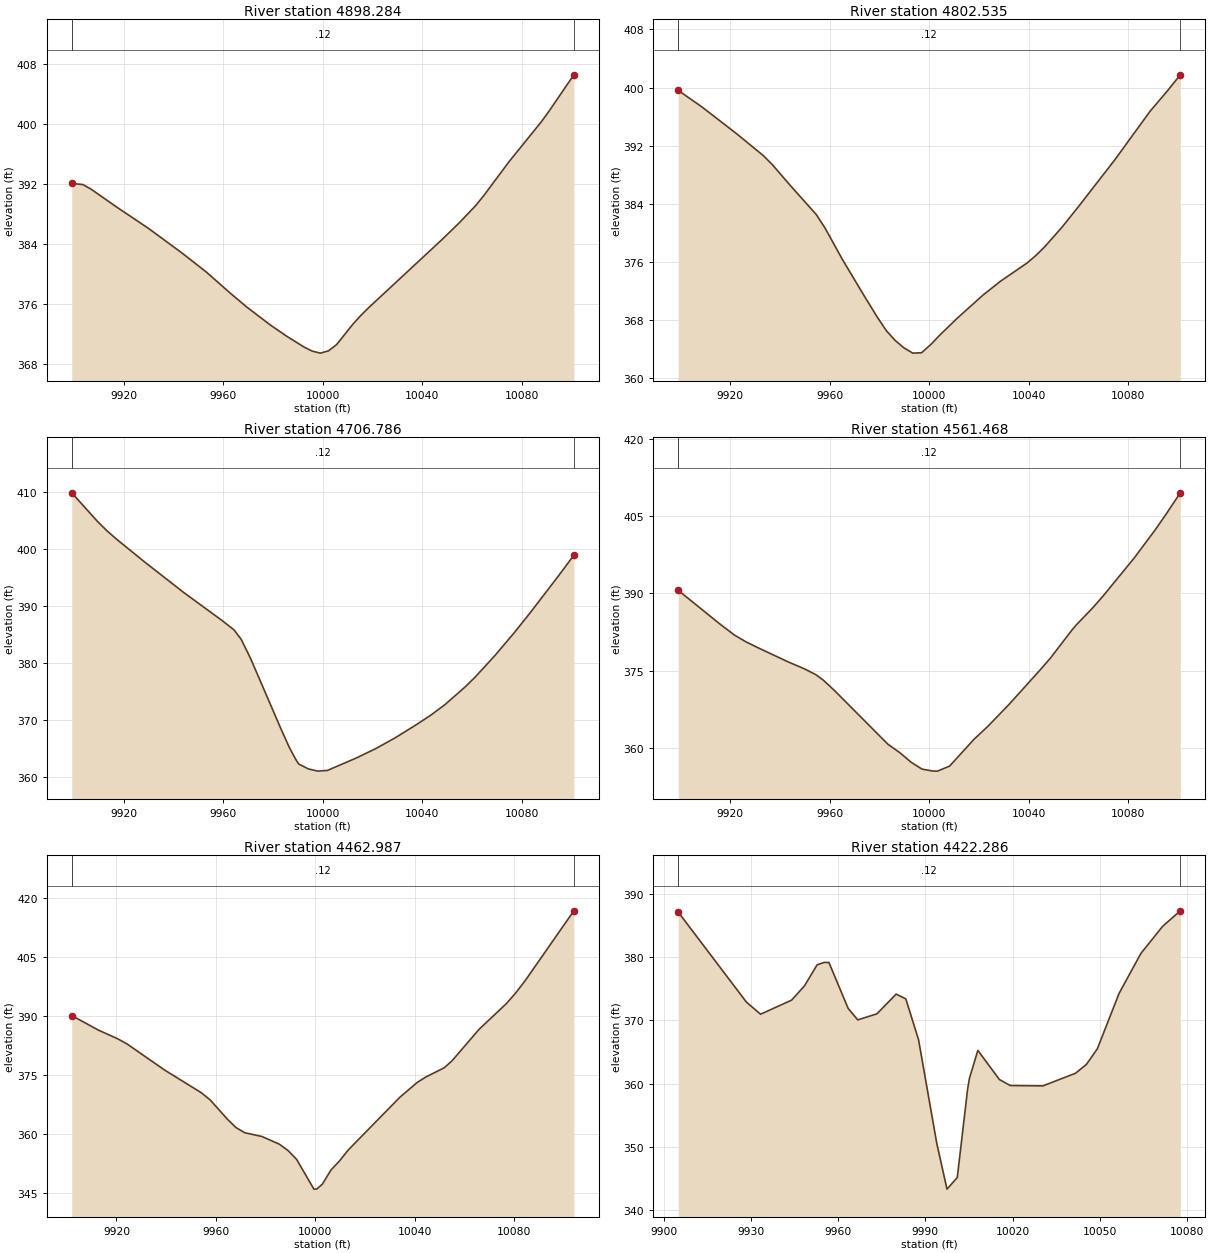
Type RM Length L Ch R = 1 ,4898.284,95.749300,95.749300,95.749300
XS GIS Cut Line= 6
1235977.27149518840527.2453659671235921.82756332840533.678024572
1235877.71623112840535.9435741351235875.71750541840536.014957254
1235831.21262743840538.4658653481235776.38507342840546.396252031
#Sta/Elev= 27
9899.015392.10269903.435391.95979906.738391.35359916.646389.05219929.858386.1133
9943.069382.89639952.978380.33239962.843377.45139969.413375.61649979.269373.1331
9985.839371.6488 9992.41370.29239995.695 369.744 9998.98369.471810002.26 369.772
10005.55370.612310012.12373.343810015.41374.544610018.69375.612210048.29384.7277
10054.92386.867110061.55389.173610064.86390.533310074.81394.967310088.07400.4022
10091.38401.930710100.97406.5918
#Mann= 3 , 0 , 0
9899.015    0.12       09899.015    0.12       010100.97    0.12       0
#XS Ineff= 2 , 0
       0                               0
Bank Sta=9899.015,10100.97
Exp/Cntr=0.3,0.1

Type RM Length L Ch R = 1 ,4802.535,95.749300,95.749300,95.749300
XS GIS Cut Line= 4
1235948.99136038840407.5119742541235856.09925127 840444.51465913
1235854.21686195840445.1903886941235761.44912852840482.516745958
#Sta/Elev= 30
9899.009399.6026 9908.61397.31189922.736393.56749933.331390.59399936.862389.3767
9943.926386.5697 9954.52382.50879958.052380.65529965.076376.29879973.942371.2266
9979.241368.28079982.773366.47839986.304365.14389989.836364.12669993.367 363.403
9996.899363.451310000.69364.610610003.94365.783610011.01368.135810021.62371.3991
10028.69373.3168 10039.3375.809910042.84376.840210046.38378.027110053.45380.7729
10060.52383.803610074.67390.049210088.81396.715910095.89399.5733   10101401.7499
#Mann= 3 , 0 , 0
9899.009    0.12       09899.009    0.12       0   10101    0.12       0
#XS Ineff= 2 , 0
       0                               0
Bank Sta=9899.009,10101
Exp/Cntr=0.3,0.1

Type RM Length L Ch R = 1 ,4706.786,145.317600,145.317600,145.317600
XS GIS Cut Line= 5
1235899.61104693840305.7721735331235814.56658781840358.374432639
1235812.83903003840359.382174743 1235798.2275011840368.430033426
1235730.22597677840415.685283696
#Sta/Elev= 30
9899.002409.83699909.292404.8477 9913.15403.18049917.008401.70769928.581 397.611
9944.012392.35989959.442387.43899964.255385.79529967.158384.13599971.016380.6983
9982.966 368.6119986.446365.23459989.203362.99199990.304362.25289994.162361.3972
9998.019361.002410001.85 361.12210013.42363.295110021.25364.943910029.24366.8782
10037.53369.126710043.28370.765910049.21372.6981 10057.2375.7555 10061.2 377.465
10069.19381.255210077.18385.377710083.52388.842710095.02395.385910100.99398.8853
#Mann= 3 , 0 , 0
9899.002    0.12       09899.002    0.12       010100.99    0.12       0
#XS Ineff= 2 , 0
       0                               0
Bank Sta=9899.002,10100.99
Exp/Cntr=0.3,0.1

Type RM Length L Ch R = 1 ,4561.468,98.481100,98.481100,98.481100
XS GIS Cut Line= 6
1235801.04694822840176.5900879141235753.13359535840223.940313913
1235728.59702196840245.4473255811235727.05316153840246.718740133
1235706.57029001840265.3063429131235661.44786447840321.782356339
#Sta/Elev= 30
9899.009390.6038 9915.73384.08129921.586381.93359926.254380.60289930.921379.4979
9943.406376.67029949.591375.39649954.259374.25929957.244373.21489961.856371.1478
9983.319360.72879988.296359.0202 9992.64357.22999997.003355.893810001.32355.5117
10003.26355.490910008.14356.4612 10017.9361.639210023.47364.1568   10032368.4147
 10044.6375.1655 10048.8 377.503 10057.2382.793710059.29383.9865 10065.6 387.143
10069.81389.4559 10082.4396.8897 10090.8402.321610094.99405.233210100.95409.5495
#Mann= 3 , 0 , 0
9899.009    0.12       09899.009    0.12       010100.95    0.12       0
#XS Ineff= 2 , 0
       0                               0
Bank Sta=9899.009,10100.95
Exp/Cntr=0.3,0.1

Type RM Length L Ch R = 1 ,4462.987,40.701000,40.701000,40.701000
XS GIS Cut Line= 6
1235679.72284054840124.2881945731235664.65321046 840148.81893014
1235652.54213605840172.8097643461235622.32043944840260.691832002
1235610.21735135840286.3965794631235597.69107306840307.886440294
#Sta/Elev= 30
9902.025390.18319912.725386.49879920.426384.31179924.276382.97269939.274376.3832
9953.975370.6435 9957.65368.78639964.612363.86559968.093361.72459971.573360.4289
9978.533359.46139985.493357.51759988.973355.91379992.453353.65429999.413346.0938
10000.59346.128310002.85347.384910006.27350.954210009.73353.2688 10013.2356.0295
10034.02369.460810040.96373.198110044.43374.582810051.81 376.91610055.02378.7422
 10065.9386.737710076.78393.203810080.47395.865810084.27 398.96410103.95416.7981
#Mann= 3 , 0 , 0
9902.025    0.12       09902.025    0.12       010103.95    0.12       0
#XS Ineff= 2 , 0
       09969.166                       0
Bank Sta=9902.025,10103.95
Exp/Cntr=0.3,0.1

Type RM Length L Ch R = 1 ,4422.286,55.368400,55.368400,55.368400
XS GIS Cut Line= 5
1235647.29805208840120.8547002371235610.31888541840154.708866903
1235607.19388541 840182.313033571235597.29805208840206.792200237
1235564.48555208 840266.68803357
#Sta/Elev= 30
9905.044387.16299928.489372.90579933.347370.99199944.019373.21869948.467375.4908
9952.782378.80619955.179379.18889956.852379.18289963.456371.92059966.757370.0948
9973.361371.05579979.965374.17449983.288373.42659987.674366.93729993.905350.6084
9997.443 343.29710000.98345.131410004.52359.072610005.18360.869810008.06365.2607
10015.47360.648310019.21359.699210030.43359.643510041.65361.649410045.39 363.048
10049.14365.521710056.62374.2981 10064.1380.611110071.58384.907710077.66387.3613
#Mann= 3 , 0 , 0
9905.044    0.12       09905.044    0.12       010077.66    0.12       0
#XS Ineff= 2 , 0
       09984.763                       0
Bank Sta=9905.044,10077.66
Exp/Cntr=0.3,0.1

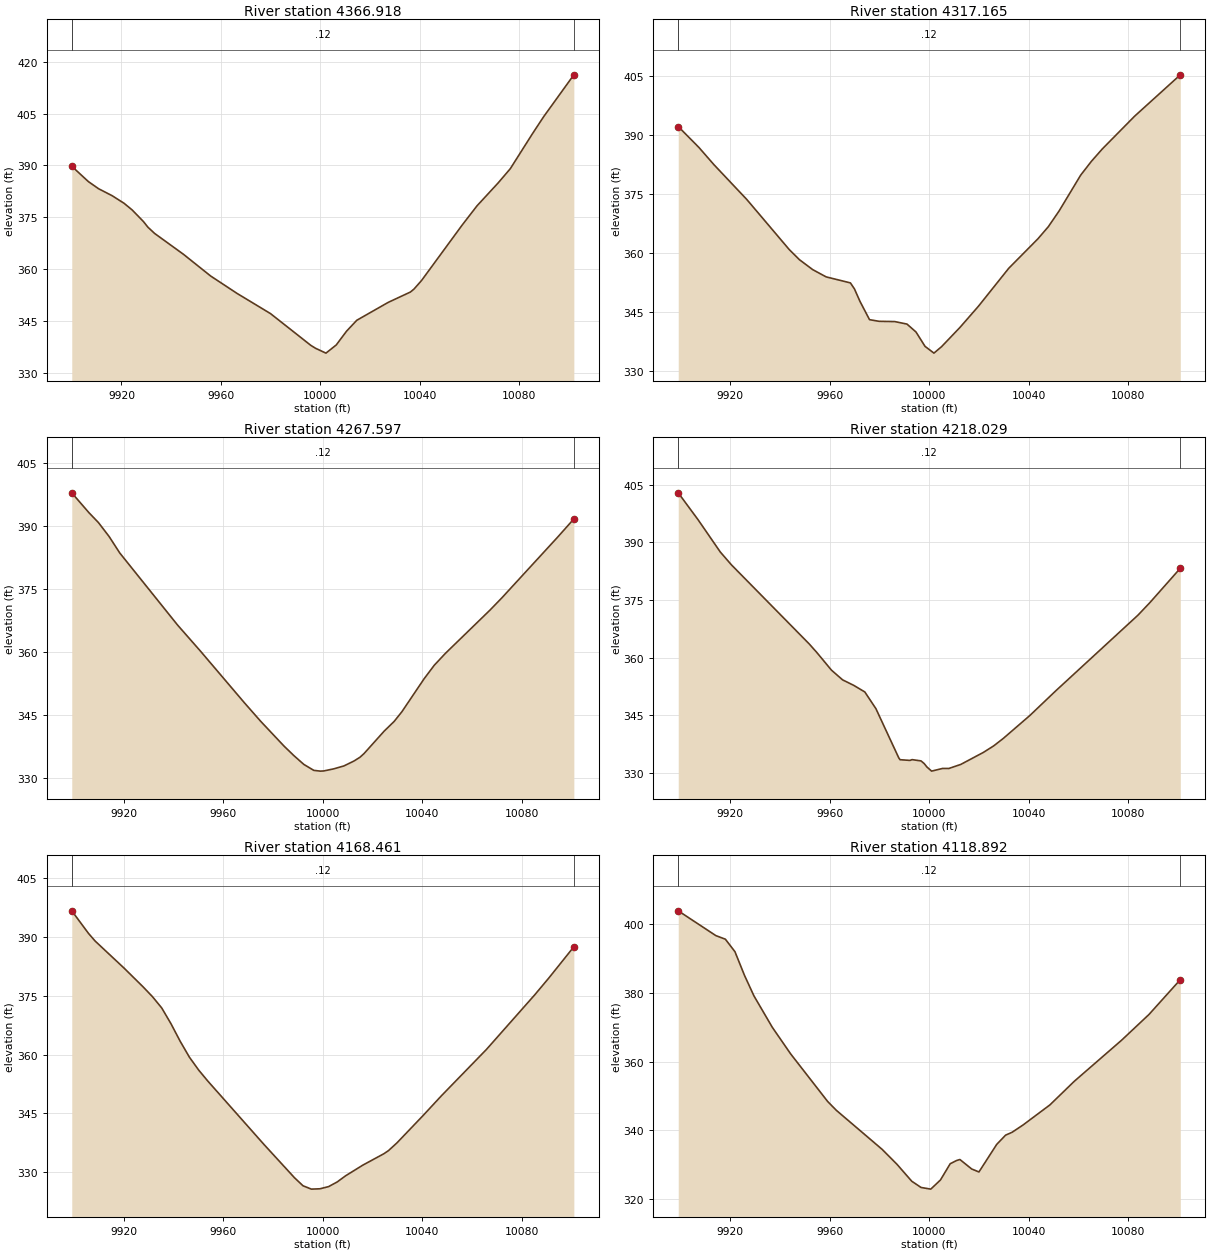
Type RM Length L Ch R = 1 ,4366.918,49.752500,49.752500,49.752500
XS GIS Cut Line= 6
1235626.41438376840089.4828386821235580.77575305840137.855908555
1235560.47759579840164.4607924921235559.19722703 840165.99723509
1235545.49938524840183.7828359351235492.93428916840240.783539369
#Sta/Elev= 30
9900.008389.76749906.686385.34339910.777383.28279916.248 381.2649921.029379.0785
9924.309377.13999928.819373.8095 9930.59372.2003 9933.33370.36479944.933364.3354
9955.883358.05579966.512353.0269 9979.96347.19399996.187 338.0149998.054337.1856
10002.25 335.78310006.39338.141410010.53342.121310014.67345.2808 10027.3350.4455
10036.23353.434110037.66354.286610040.69356.750610057.01 372.74910063.01 378.335
10071.53384.9669 10076.4389.062410085.32399.178110089.78404.050910101.96416.1835
#Mann= 3 , 0 , 0
9900.008    0.12       09900.008    0.12       010101.96    0.12       0
#XS Ineff= 2 , 0
       0                               0
Bank Sta=9900.008,10101.96
Exp/Cntr=0.3,0.1

Type RM Length L Ch R = 1 ,4317.165,49.568300,49.568300,49.568300
XS GIS Cut Line= 6
1235609.53350813840068.8193800631235558.56699673840111.446624501
1235540.98823839840122.1251640331235510.57800218840136.705959604
1235489.17709604840150.6871372681235447.20915645840187.065809593
#Sta/Elev= 30
9899.034392.11739907.307386.82479913.379382.41919926.614373.54129943.633 360.824
 9947.76 358.2229953.132355.67539958.503353.84129968.276352.30379969.903350.7657
9972.115347.60839975.954342.94759979.792342.52649986.092  342.46 9991.02341.8219
9994.647339.80329998.274336.156110001.86334.427110004.96336.090710012.37341.0049
10019.78346.384910031.93356.020810043.69363.544310047.85366.611210052.19370.6216
10060.87379.745310065.21383.283710069.56386.411510082.58394.765910100.93 405.284
#Mann= 3 , 0 , 0
9899.034    0.12       09899.034    0.12       010100.93    0.12       0
#XS Ineff= 2 , 0
       0                               0
Bank Sta=9899.034,10100.93
Exp/Cntr=0.3,0.1

Type RM Length L Ch R = 1 ,4267.597,49.568300,49.568300,49.568300
XS GIS Cut Line= 6
1235584.11776518840024.0167156521235544.52335534840057.266227254
1235504.83106935840084.7315388341235503.23874499840085.941705417
1235467.31083254840111.7131023491235426.92275093840150.104090987
#Sta/Elev= 30
9899.028397.85859905.873393.1711 9909.76390.76859914.044387.45929918.328383.5367
9941.585366.36579950.732360.19919968.432347.87569974.989343.45989984.391337.5444
 9988.38 335.263 9992.37333.1769 9996.36331.7679    9999331.584110000.39 331.628
10004.44332.135810008.48 332.82110012.52333.991810014.89334.872410016.56335.7635
10024.63341.089210028.67343.416910031.77345.713410040.78353.625710044.82356.8031
 10049.3359.633310067.18 369.90710071.94372.812410094.56387.393110100.94391.6387
#Mann= 3 , 0 , 0
9899.028    0.12       09899.028    0.12       010100.94    0.12       0
#XS Ineff= 2 , 0
       0                               0
Bank Sta=9899.028,10100.94
Exp/Cntr=0.3,0.1

Type RM Length L Ch R = 1 ,4218.029,49.568200,49.568200,49.568200
XS GIS Cut Line= 6
1235544.81822324839973.3465313781235490.78914176840031.725961613
 1235475.7464927840045.550917277 1235474.1190258840046.713393713
1235461.57542494840058.4122131541235410.90127917840123.893338142
#Sta/Elev= 30
9899.025402.88089907.009395.88029915.949387.48579920.419384.15369951.711363.5789
  9954.7361.41019960.652356.76659965.122354.24619969.592 352.8189974.063351.0995
9978.533346.74599987.741333.93219988.227333.47929992.197333.29879993.075333.4979
9996.653333.17269997.924332.4897    9999331.616510000.91330.509910005.38331.2133
10007.85331.197510012.66332.253210021.71335.363510025.86337.0582 10029.7338.9812
10040.42344.962810050.75351.325510083.94371.079410088.67374.301110100.95383.2664
#Mann= 3 , 0 , 0
9899.025    0.12       09899.025    0.12       010100.95    0.12       0
#XS Ineff= 2 , 0
       0                               0
Bank Sta=9899.025,10100.95
Exp/Cntr=0.3,0.1

Type RM Length L Ch R = 1 ,4168.461,49.568300,49.568300,49.568300
XS GIS Cut Line= 6
1235474.56223615839935.1915436661235447.88521201839980.973137214
1235438.78204309840003.539930966 1235421.3034032840061.533298156
1235409.11225886840086.4959576661235390.23673603840117.352278873
#Sta/Elev= 30
9899.036396.5666  9905.8 390.7949908.448388.86589920.137381.94899927.772377.1825
9931.487374.72189935.203371.85649938.918367.85739942.634363.37439946.349359.3194
9950.065 356.0519953.698353.2797  9976.4337.0644  9988.6328.64589992.005326.6079
 9995.41325.74729998.814325.832910002.31326.385110005.75327.562310009.18329.1478
10016.05331.840210024.58334.765910026.36335.526910029.79337.5067 10040.3344.4625
 10047.6349.446410065.79361.291510085.14 375.13310090.94379.510610100.94387.4184
#Mann= 3 , 0 , 0
9899.036    0.12       09899.036    0.12       010100.94    0.12       0
#XS Ineff= 2 , 0
       0                               0
Bank Sta=9899.036,10100.94
Exp/Cntr=0.3,0.1

Type RM Length L Ch R = 1 ,4118.892,18.326200,18.326200,18.326200
XS GIS Cut Line= 6
1235437.90483647839920.3914233191235422.59675473839945.370921089
1235398.14538713839993.2488355891235378.44434372840023.484088341
 1235358.8361451840069.3077947461235343.91566042840098.678847302
#Sta/Elev= 30
9899.026403.74759914.136396.55929917.984 395.5099921.832391.89129925.679385.0016
9929.476379.05399936.844369.94879944.212362.24049959.148348.37339962.631345.8164
9981.051334.48189986.976330.18159992.939325.24299996.698323.4246 10000.6322.9466
 10004.5325.611310008.41330.315310011.03331.265910012.32331.542410017.06328.7889
10019.97327.931310027.11335.930110030.68338.611310033.31339.456110037.81341.6215
10048.52347.403810058.33354.265910077.35366.184610088.39373.678710100.96383.7613
#Mann= 3 , 0 , 0
9899.026    0.12       09899.026    0.12       010100.96    0.12       0
#XS Ineff= 2 , 0
       09967.409        10012.93       0
Bank Sta=9899.026,10100.96
Exp/Cntr=0.3,0.1

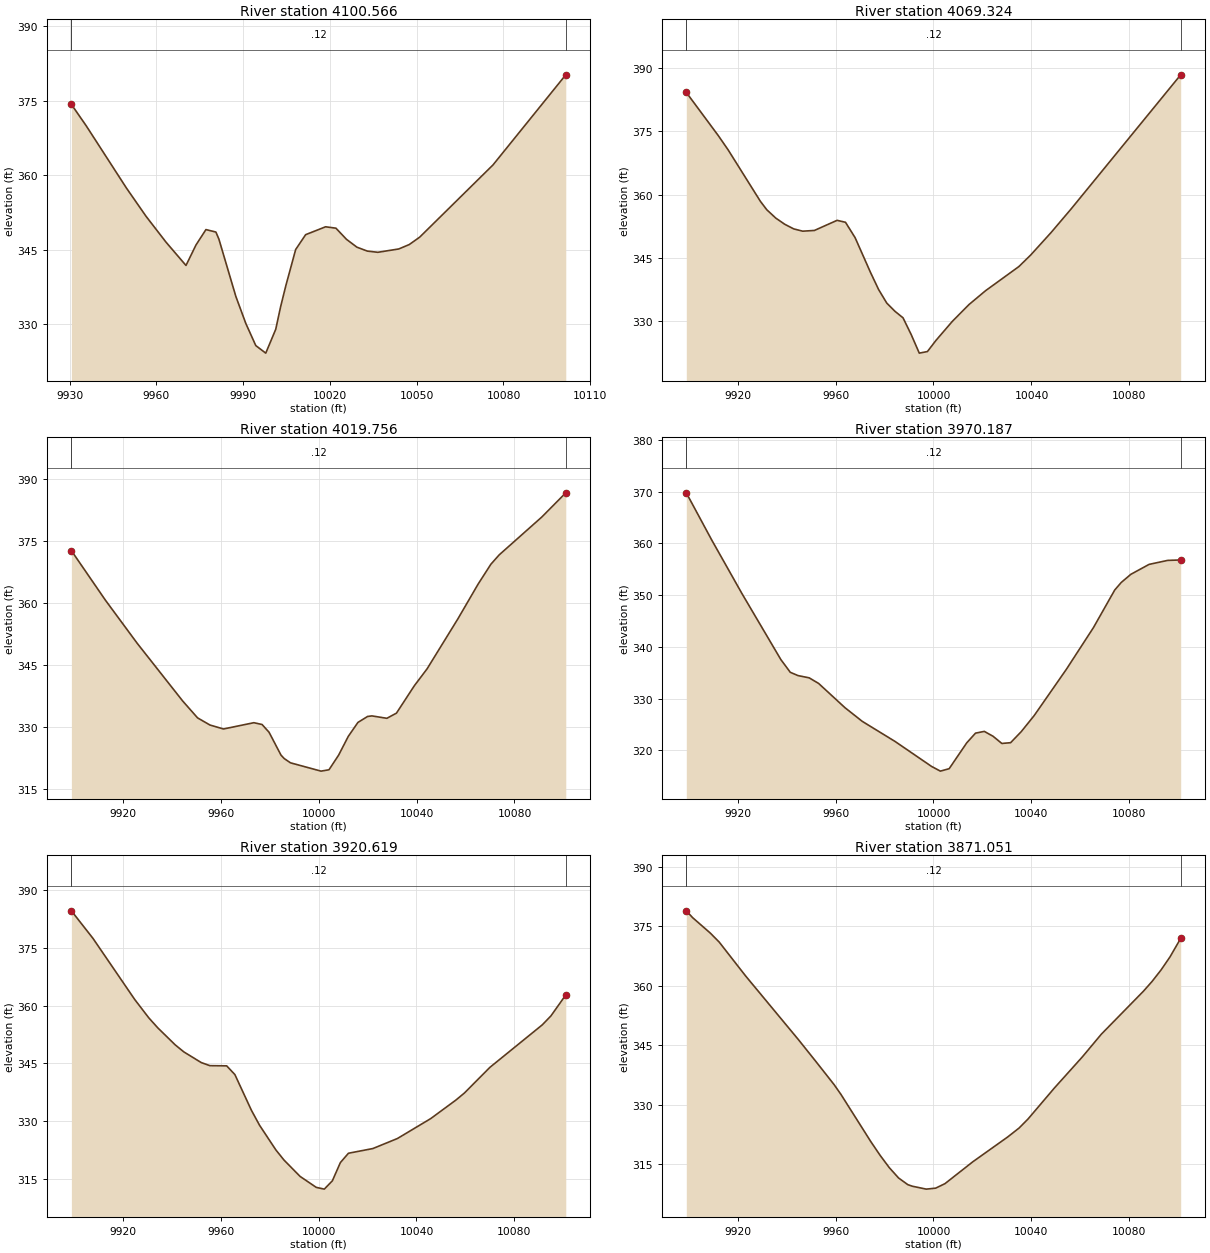
Type RM Length L Ch R = 1 ,4100.566,31.242100,31.242100,31.242100
XS GIS Cut Line= 3
1235394.74760911839931.6569956391235367.46965256 840015.99970755
 1235332.6816369840090.597967863
#Sta/Elev= 30
9930.594374.29079935.742369.96049949.622 357.4549956.431351.74569963.327346.5481
9970.223341.86369973.671 345.9759977.119349.08549980.568348.59019981.607 347.161
9987.464335.63199990.912330.1881 9994.36325.73349997.808324.216810001.26329.0192
10002.93 333.516 10004.7 337.68510008.15345.0745 10011.6348.0631 10018.5349.6497
10022.08349.3657 10025.7347.134310029.32345.545510032.94344.753710036.56344.5144
 10043.8 345.18410047.42346.069310051.04347.563710076.38362.097510101.55380.2383
#Mann= 3 , 0 , 0
9930.594    0.12       09930.594    0.12       010101.55    0.12       0
#XS Ineff= 2 , 0
       09986.206        10011.49       0
Bank Sta=9930.594,10101.55
Exp/Cntr=0.3,0.1

Type RM Length L Ch R = 1 ,4069.324,49.568300,49.568300,49.568300
XS GIS Cut Line= 6
1235381.64444684839909.4501893461235364.24762949839934.214617364
1235354.47921113839953.9614389121235335.63545421840033.477651898
1235323.70706437840061.4475525091235305.49133055840093.971937193
#Sta/Elev= 30
9899.087384.22669912.164373.97459916.174370.60479929.351358.40139931.962356.4063
9935.623354.43679939.283352.97229942.943351.87979946.604351.33829951.382351.5085
9960.644353.90639964.081353.44539968.004349.80129974.297341.55379977.616337.4902
9980.934334.29139984.253332.35849987.571 330.799 9990.89326.84899994.208322.4331
9997.527 322.808   10001325.437210007.67329.941110014.45333.920910021.24337.2167
10034.88342.956610039.67345.674210048.03351.026310056.28356.667710100.93388.3966
#Mann= 3 , 0 , 0
9899.087    0.12       09899.087    0.12       010100.93    0.12       0
#XS Ineff= 2 , 0
       09978.719        10013.72       0
Bank Sta=9899.087,10100.93
Exp/Cntr=0.3,0.1

Type RM Length L Ch R = 1 ,4019.756,49.568300,49.568300,49.568300
XS GIS Cut Line= 6
1235361.89093837839903.6842277761235337.47562657839928.381046214
1235321.40239396839947.1786238561235299.98735925839981.530784736
1235279.54521716840011.8959423851235238.38744707840062.646872987
#Sta/Elev= 30
9899.059372.63729912.987360.61269925.985350.15319944.542336.18849950.589332.1233
9955.637330.3922 9961.18329.42989973.584330.9514 9976.93330.51489979.786328.6398
9984.662323.09629985.987322.26239988.528 321.233   10001319.218510004.26319.5471
 10008.2323.097510012.14327.638310016.07331.010510020.01332.4607 10021.8332.6001
10027.89332.016710031.82333.273710039.11339.900910044.32344.000210056.89356.1035
10065.16364.530310070.37369.341210073.79371.6257 10091.2380.801910100.96386.6483
#Mann= 3 , 0 , 0
9899.059    0.12       09899.059    0.12       010100.96    0.12       0
#XS Ineff= 2 , 0
       09971.569                       0
Bank Sta=9899.059,10100.96
Exp/Cntr=0.3,0.1

Type RM Length L Ch R = 1 ,3970.187,49.568200,49.568200,49.568200
XS GIS Cut Line= 6
 1235354.5477406839897.1581860411235332.12673596839914.261482034
1235308.99139082839928.5598903061235265.87687806839946.092628555
1235234.00828164839960.1614289671235177.56478156839992.633448421
#Sta/Elev= 30
 9899.06369.74739909.507360.57939921.886350.20739937.665337.54659941.522335.0824
9944.702334.44369949.235334.01269953.092332.9326 9963.83328.25729970.914325.6083
9984.372 321.707 9999.25316.892110002.81315.9944 10006.4316.462910013.57321.4507
10017.16323.331410020.74323.670210024.33322.727810027.91321.3395 10031.5321.4873
10035.84323.622510041.13326.731710054.29335.679710065.33 343.72310074.03350.9883
10076.68352.438510080.61354.011310088.04355.924910095.61356.694310100.95356.7819
#Mann= 3 , 0 , 0
 9899.06    0.12       0 9899.06    0.12       010100.95    0.12       0
#XS Ineff= 2 , 0
       09963.277        10034.48       0
Bank Sta=9899.06,10100.95
Exp/Cntr=0.3,0.1

Type RM Length L Ch R = 1 ,3920.619,49.568300,49.568300,49.568300
XS GIS Cut Line= 6
1235360.45904918839864.5389799131235330.42145416839881.931399888
1235307.47709937839891.1255803761235286.39880308839895.835243029
1235229.51133315839902.5784037821235170.06990493839924.665083843
#Sta/Elev= 30
9899.078384.60319907.925377.41739924.944361.56979930.671356.81329934.417354.1664
9941.486349.7751 9945.02347.94799952.089345.18839955.623344.38279962.488344.3321
9965.849342.05839972.573332.81789975.935328.87929982.605322.46929985.896319.8589
9992.479315.60529999.062312.763710002.35312.306710005.64314.459510008.93319.2146
10012.22321.626910022.19322.8487 10032.2325.4496 10045.8330.623910056.13335.4576
10059.57337.277610069.97343.934310091.35354.972910094.91357.315610100.96362.7476
#Mann= 3 , 0 , 0
9899.078    0.12       09899.078    0.12       010100.96    0.12       0
#XS Ineff= 2 , 0
       09972.858        10048.55       0
Bank Sta=9899.078,10100.96
Exp/Cntr=0.3,0.1

Type RM Length L Ch R = 1 ,3871.051,49.568300,49.568300,49.568300
XS GIS Cut Line= 6
1235338.75333486839807.0824668371235281.36968475839833.455016299
1235249.41217186839851.7531265611235247.72119408839852.821112593
1235221.47806063839868.2436940461235158.55469662839897.859395032
#Sta/Elev= 30
9899.021378.86219901.612377.13979908.834373.25279912.444371.00419923.277362.4455
9944.941346.33919952.162340.76549959.384335.11179962.175332.65429974.375320.7708
9978.186317.30369981.936314.19759985.717311.60259989.497309.91829991.391 309.511
9997.058 308.78710000.89309.0339 10004.7310.171410016.11315.693710030.28 321.906
10034.96324.169210038.59326.425310049.47334.307410060.88342.133510068.58347.8107
10085.73 358.60310089.36361.135410092.98363.993410096.61367.258910100.98371.9186
#Mann= 3 , 0 , 0
9899.021    0.12       09899.021    0.12       010100.98    0.12       0
#XS Ineff= 2 , 0
       0                               0
Bank Sta=9899.021,10100.98
Exp/Cntr=0.3,0.1