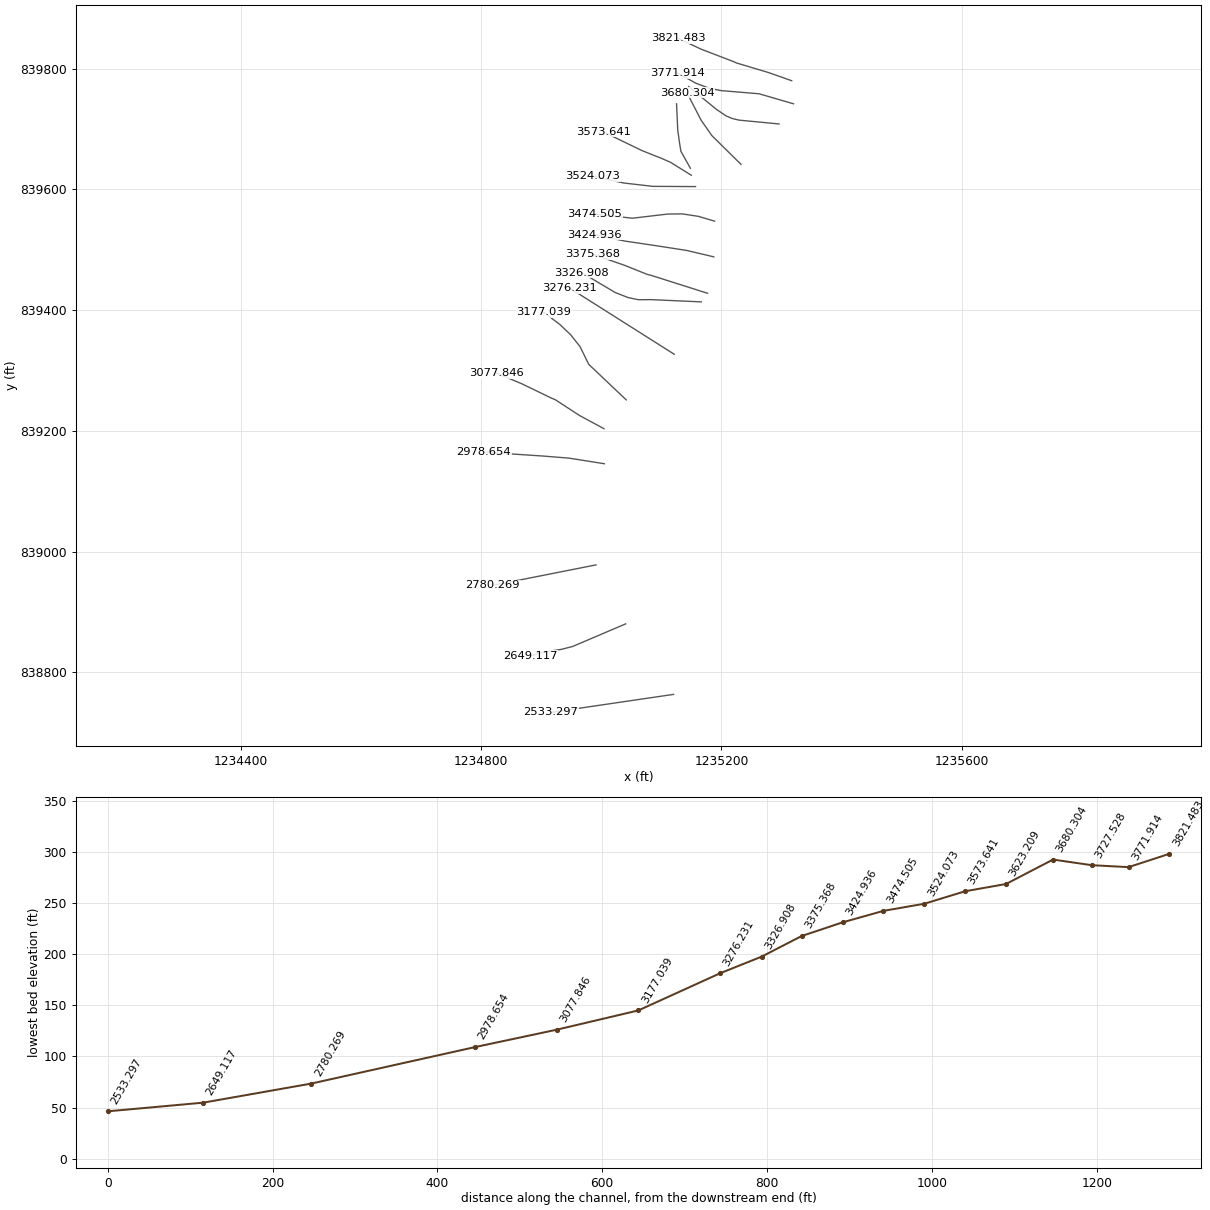
HEC-RAS study 21_ras.prj: 21

--- 21_ras.g01 (geometry) --- (continued)

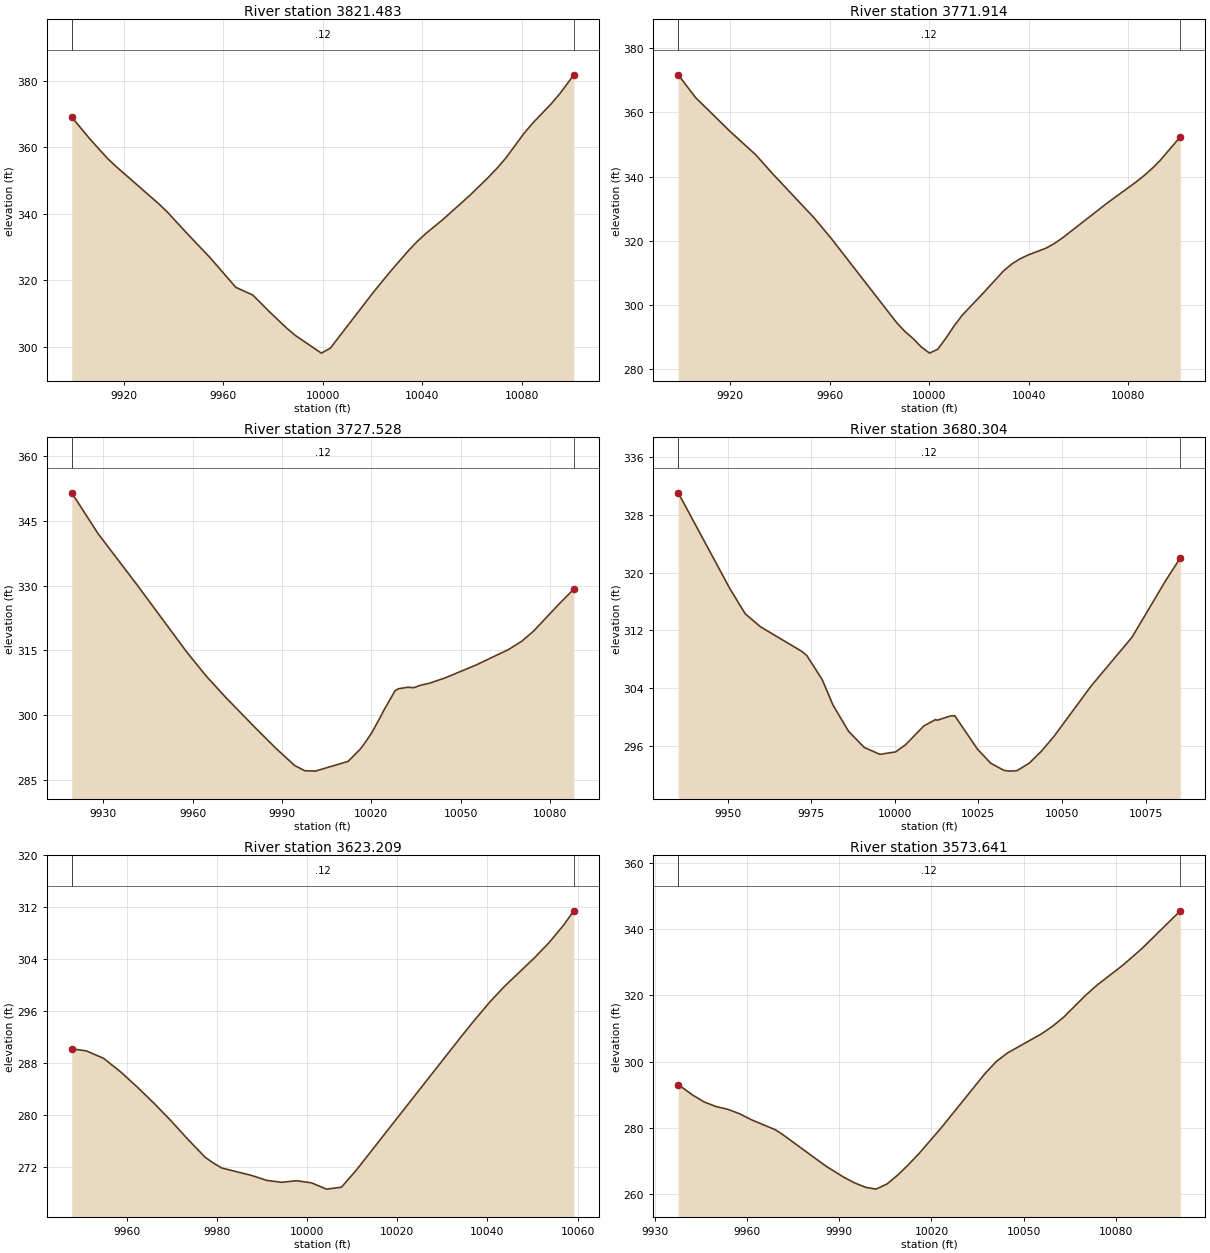
Type RM Length L Ch R = 1 ,3821.483,49.568300,49.568300,49.568300
XS GIS Cut Line= 6
1235317.03375354839780.1289217411235277.26798218839794.007641581
1235225.06226198839809.5467628341235220.15189929839811.786404377
1235165.96431168839832.4810786451235128.00837808839850.386872285
#Sta/Elev= 30
9899.014369.08059906.302362.50759913.252 356.7519916.727 354.2989934.102342.9459
9937.576 340.4429944.476334.82389954.745326.73299965.014317.8846 9971.86315.5666
9978.706310.42779985.553305.56919988.976303.40069999.415298.107610002.99299.5733
10020.55316.617610027.58323.0254 10034.6329.038210038.11331.785210041.63334.1906
10048.65338.505510059.19345.592910066.45350.871610070.07353.7125 10073.7356.8494
10080.96364.225110084.58367.382710091.84373.055610095.47376.247810100.97381.7888
#Mann= 3 , 0 , 0
9899.014    0.12       09899.014    0.12       010100.97    0.12       0
#XS Ineff= 2 , 0
       0                               0
Bank Sta=9899.014,10100.97
Exp/Cntr=0.3,0.1

Type RM Length L Ch R = 1 ,3771.914,44.386400,44.386400,44.386400
XS GIS Cut Line= 6
1235320.01315118839741.8989455331235262.88472561839758.455940818
1235199.92237056 839763.695209861235180.55124336839767.341005469
1235157.49708503839775.9933989311235127.06894248839792.884695257
#Sta/Elev= 30
 9899.06371.7044 9906.02364.63949919.902 354.0959930.234346.81049936.984 340.953
9953.858327.0512 9960.56320.8085 9986.92294.53679990.215291.8327 9993.51289.6084
9996.805286.9963 10000.1285.089710003.38286.292610006.67289.717210009.96293.5445
10013.25296.893510021.79303.855910029.81310.648610033.15 312.81910036.49314.4528
10039.83315.662910046.89317.748510050.26319.172510053.76321.077410071.65331.8641
 10082.9338.205810086.66340.523210090.41343.161510092.76345.017710100.93352.4008
#Mann= 3 , 0 , 0
 9899.06    0.12       0 9899.06    0.12       010100.93    0.12       0
#XS Ineff= 2 , 0
       0                10025.53       0
Bank Sta=9899.06,10100.93
Exp/Cntr=0.3,0.1

Type RM Length L Ch R = 1 ,3727.528,47.223700,47.223700,47.223700
XS GIS Cut Line= 6
1235295.96124652839708.4878020881235229.50593733839714.825157773
 1235218.1228253839717.5163853471235207.91424086839721.819784254
1235191.54801006 839732.795734141235145.49771528839770.425661448
#Sta/Elev= 30
9919.343351.49639928.158342.06069941.341330.10619957.819 314.7329964.411309.1084
9971.002304.13189980.889297.1174  9988.1 292.1619994.251288.27989997.627287.0796
10001.18  286.9810012.19289.240810016.14 291.96710017.43293.114910020.09295.8182
10023.32299.853610024.04300.875510027.99305.628910029.13306.066910032.18306.4215
10034.32306.336610036.42 306.866 10039.5307.352610044.69 308.56710055.06 311.537
10066.08 315.16310070.61 317.12210074.55319.464610083.02325.680710088.05329.1877
#Mann= 3 , 0 , 0
9919.343    0.12       09919.343    0.12       010088.05    0.12       0
#XS Ineff= 2 , 0
       0                10022.52       0
Bank Sta=9919.343,10088.05
Exp/Cntr=0.3,0.1

Type RM Length L Ch R = 1 ,3680.304,57.094700,57.094700,57.094700
XS GIS Cut Line= 4
1235232.59319096839641.6475243111235184.08176615 839689.30617929
1235166.24902477839714.7775246041235142.74944096839760.137107644
#Sta/Elev= 30
9935.219331.04599950.672317.77079955.271  314.289959.871312.47539972.146309.0938
9973.668308.50769978.267305.19349981.509301.64629986.191297.99659990.872 295.775
9995.554294.815910000.24295.159110003.22296.152410008.68298.752810012.23299.6445
10012.68299.540810016.69300.144110017.95300.1586 10024.7295.5588 10028.7293.5845
10032.71292.592310034.32292.494910036.53 292.55510040.22293.601110043.92295.2911
10047.61 297.307 10058.7304.272310070.96311.046210080.87318.7704 10085.4322.0371
#Mann= 3 , 0 , 0
9935.219    0.12       09935.219    0.12       0 10085.4    0.12       0
#XS Ineff= 2 , 0
       09983.606        10026.07       0
Bank Sta=9935.219,10085.4
Exp/Cntr=0.3,0.1

Type RM Length L Ch R = 1 ,3623.209,49.568300,49.568300,49.568300
XS GIS Cut Line= 6
1235148.39180208839635.1371076441235132.58136933839663.320649768
1235129.61613362 839681.952566741235129.46274068839683.946675715
1235127.39330479839697.9193765581235125.38832985839741.907940977
#Sta/Elev= 27
9947.818 290.208  9951.1289.86549954.862 288.7369958.624 286.6689962.385284.2891
9966.147281.75159969.909279.05779973.671276.18559977.433273.48129979.304272.5779
 9981.07271.85349987.715 270.7029991.037269.94359994.359269.64969997.681269.8885
10000.98 269.564 10004.3268.597810007.62268.891510010.93271.532910033.96291.8841
10037.25294.717210040.53297.407310043.82299.843610050.39304.179510053.67306.5494
10056.95309.291410059.16311.4378
#Mann= 3 , 0 , 0
9947.818    0.12       09947.818    0.12       010059.16    0.12       0
#XS Ineff= 2 , 0
       0                10020.15       0
Bank Sta=9947.818,10059.16
Exp/Cntr=0.3,0.1

Type RM Length L Ch R = 1 ,3573.641,49.568300,49.568300,49.568300
XS GIS Cut Line= 6
1235149.98323726839623.5051631991235115.46375513839644.919755429
1235096.42294838839653.1807199921235094.51496096839653.780373242
1235067.75278203839664.4146299241235003.62576671839695.315199957
#Sta/Elev= 30
9937.622293.07939942.179289.9912 9946.04287.82859949.901 286.4519953.762285.6046
9957.623284.25099961.484282.42739969.206279.4427 9971.34278.17579985.586268.5266
 9991.33 265.2019994.906263.44359998.482262.096110001.97261.5215 10005.5263.0457
10009.03265.757810012.56268.939310016.09272.386610023.15279.972210037.51 296.475
10041.15 300.06310044.79302.625910055.71308.318210059.36310.6308   10063313.3847
10070.28320.106510073.92323.097310082.31329.108710088.49334.112110100.98345.4947
#Mann= 3 , 0 , 0
9937.622    0.12       09937.622    0.12       010100.98    0.12       0
#XS Ineff= 2 , 0
       0                               0
Bank Sta=9937.622,10100.98
Exp/Cntr=0.3,0.1

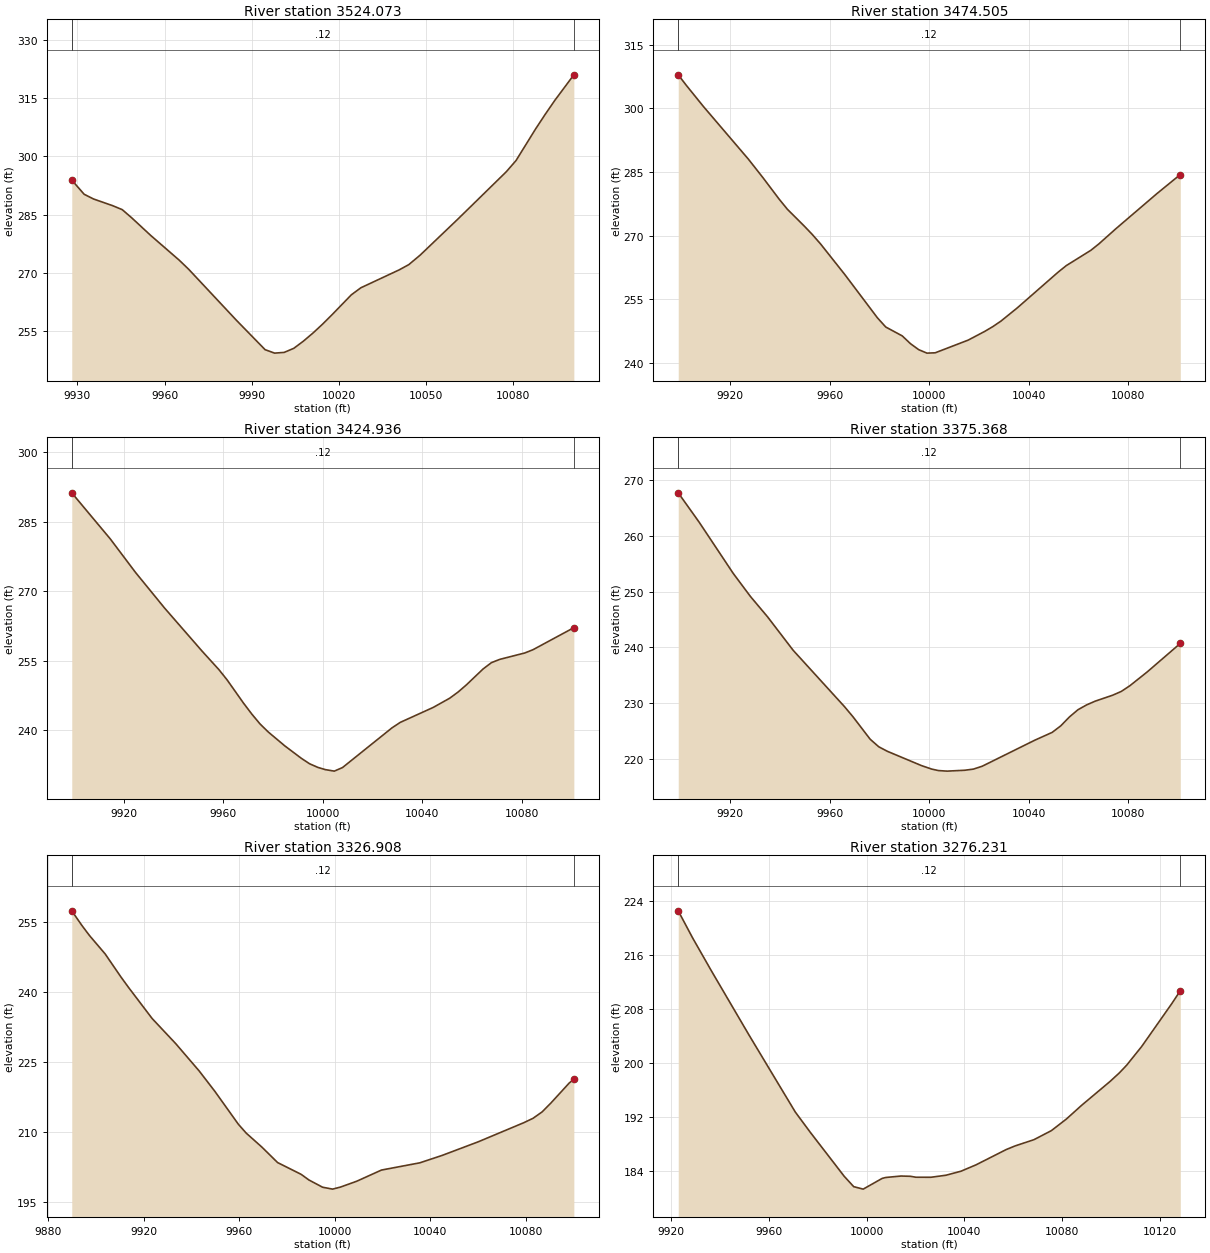
Type RM Length L Ch R = 1 ,3524.073,49.568300,49.568300,49.568300
XS GIS Cut Line= 5
1235156.92768171839604.7551631991235085.95593839839605.143798758
1235083.96963719839605.3774813121235037.25540074839610.718366152
1234985.57530252839622.207383464
#Sta/Elev= 30
9928.027293.91529932.283290.25969935.564289.02499942.125287.30979945.406286.2922
9948.687284.17299955.249279.62149965.092273.22889968.372270.86039984.777257.7422
 9994.62250.1916  9997.9249.3026 10001.2 249.493 10004.5250.5424 10007.8252.3844
 10011.1254.475310014.41256.770610017.71259.228910024.31264.324810027.61266.1528
10040.82270.770510044.12272.121810048.02 274.56410060.86283.736910077.66296.0343
10081.03298.929410087.75307.049410091.11310.874310094.47314.520210100.96321.0431
#Mann= 3 , 0 , 0
9928.027    0.12       09928.027    0.12       010100.96    0.12       0
#XS Ineff= 2 , 0
       0                               0
Bank Sta=9928.027,10100.96
Exp/Cntr=0.3,0.1

Type RM Length L Ch R = 1 ,3474.505,49.568300,49.568300,49.568300
XS GIS Cut Line= 6
1235188.68186015839547.4912328121235161.65117564839555.491225919
1235134.76560735839559.5371662191235111.00718525839559.298353797
1235051.88437857839552.3810464291234989.17874517839559.277787515
#Sta/Elev= 30
9899.073307.91599902.412305.37239909.255300.41689927.263288.06089933.025283.7711
9939.661278.61849942.979276.23189949.614272.36199952.932 270.327 9956.23268.1234
9966.073260.84739979.206250.6347 9982.52248.49399989.146246.40549992.459244.5714
9995.773243.15889999.086242.3443 10002.4242.419610015.68245.414310022.27247.4494
10025.55248.583410028.84249.891710035.42253.010410051.84 261.42910055.13262.9711
10064.98266.5657 10068.3268.120610074.94 271.59810091.55279.923110100.96284.4257
#Mann= 3 , 0 , 0
9899.073    0.12       09899.073    0.12       010100.96    0.12       0
#XS Ineff= 2 , 0
       0                               0
Bank Sta=9899.073,10100.96
Exp/Cntr=0.3,0.1

Type RM Length L Ch R = 1 ,3424.936,49.568200,49.568200,49.568200
XS GIS Cut Line= 6
1235187.47045889839488.3695368811235142.65534335839498.918670124
1235089.35118558839507.1602895751235087.36920072839507.428125426
 1235038.8603309839514.599029211 1234989.0092538 839525.10962282
#Sta/Elev= 30
9899.022291.21429914.549281.2369 9924.66274.02579936.354266.33049951.526256.9777
9958.165253.06199961.485 250.8359968.125245.78729971.445243.43639974.764 241.296
9978.084239.55579984.724 236.5689991.364233.88289994.683232.70789998.003231.9253
   10001231.442910004.63231.115710007.95231.894310027.85240.468810031.17241.6446
10044.43244.876510051.08246.873710054.43248.199510057.78249.752110064.49253.1848
10067.84254.544410071.19255.250310081.25256.630310084.61257.350510100.98262.0929
#Mann= 3 , 0 , 0
9899.022    0.12       09899.022    0.12       010100.98    0.12       0
#XS Ineff= 2 , 0
       0                               0
Bank Sta=9899.022,10100.98
Exp/Cntr=0.3,0.1

Type RM Length L Ch R = 1 ,3375.368,48.460100,48.460100,48.460100
XS GIS Cut Line= 6
1235177.07744235839428.0209352281235081.73828574839458.145124352
1235079.77172174839458.5093029291235076.16695397839459.497714244
1235038.68280095839474.4202387741234985.86978614839492.764127642
#Sta/Elev= 30
9899.015267.77599907.406262.51759921.169253.2874 9928.05249.16729934.932 245.516
9945.254239.49399965.898229.37719969.339227.5401 9976.22223.52659979.661222.1747
9983.102221.36329996.864218.7889   10001218.158410003.65217.897610007.14217.7948
10014.21217.948910017.74218.156210021.27218.667910042.46223.350810049.45224.7549
10052.92225.935810056.39227.528210059.86228.834110063.34229.697410066.81230.3713
10073.76231.424810077.23 232.104 10080.7233.130710087.65235.600810100.99240.7328
#Mann= 3 , 0 , 0
9899.015    0.12       09899.015    0.12       010100.99    0.12       0
#XS Ineff= 2 , 0
       0                               0
Bank Sta=9899.015,10100.99
Exp/Cntr=0.3,0.1

Type RM Length L Ch R = 1 ,3326.908,50.676500,50.676500,50.676500
XS GIS Cut Line= 6
1235166.64990393839413.7829409771235083.07645007839417.530518769
1235061.64642039839417.4074412771235044.61164599839420.978315201
1235022.89133407 839429.504903521234967.34434837839462.394052088
#Sta/Elev= 30
9889.774257.49129893.913254.42269897.197 252.1839903.766248.23039910.334243.3121
9913.618240.9966 9923.47234.34519933.323228.96819943.175223.08069949.743218.7068
9959.596211.6318 9962.88209.73119969.448206.72699976.014203.41519985.863200.8884
9989.144199.67049994.869198.11189999.076197.702710002.43198.153810009.13199.3881
10019.55201.799310035.61203.351810044.92204.933710060.17207.885510079.24211.9856
10083.05212.913610086.86214.291110090.66216.2625 10098.3220.542810100.16221.2756
#Mann= 3 , 0 , 0
9889.774    0.12       09889.774    0.12       010100.16    0.12       0
#XS Ineff= 2 , 0
       0                               0
Bank Sta=9889.774,10100.16
Exp/Cntr=0.3,0.1

Type RM Length L Ch R = 1 ,3276.231,99.192500,99.192500,99.192500
XS GIS Cut Line= 2
1235121.48207985839327.0641909771234947.87096874839436.439190977
#Sta/Elev= 30
9923.032222.52969928.822218.57589936.578213.64649952.088204.06069970.876192.7367
9977.031189.72499990.865183.22549994.742181.6918 9998.62181.325710006.38182.9148
10007.81183.049910014.13183.264110018.01183.222110020.12183.086910026.27183.0804
10032.43183.381410038.58183.977110044.74184.921810057.05187.180710060.66187.7167
10068.42188.649410075.51 189.98310081.67 191.70610087.82193.713110099.44 197.247
10103.32198.536810106.29199.672110112.44202.446310124.75208.798610128.22210.7009
#Mann= 3 , 0 , 0
9923.032    0.12       09923.032    0.12       010128.22    0.12       0
#XS Ineff= 2 , 0
       0                               0
Bank Sta=9923.032,10128.22
Exp/Cntr=0.3,0.1

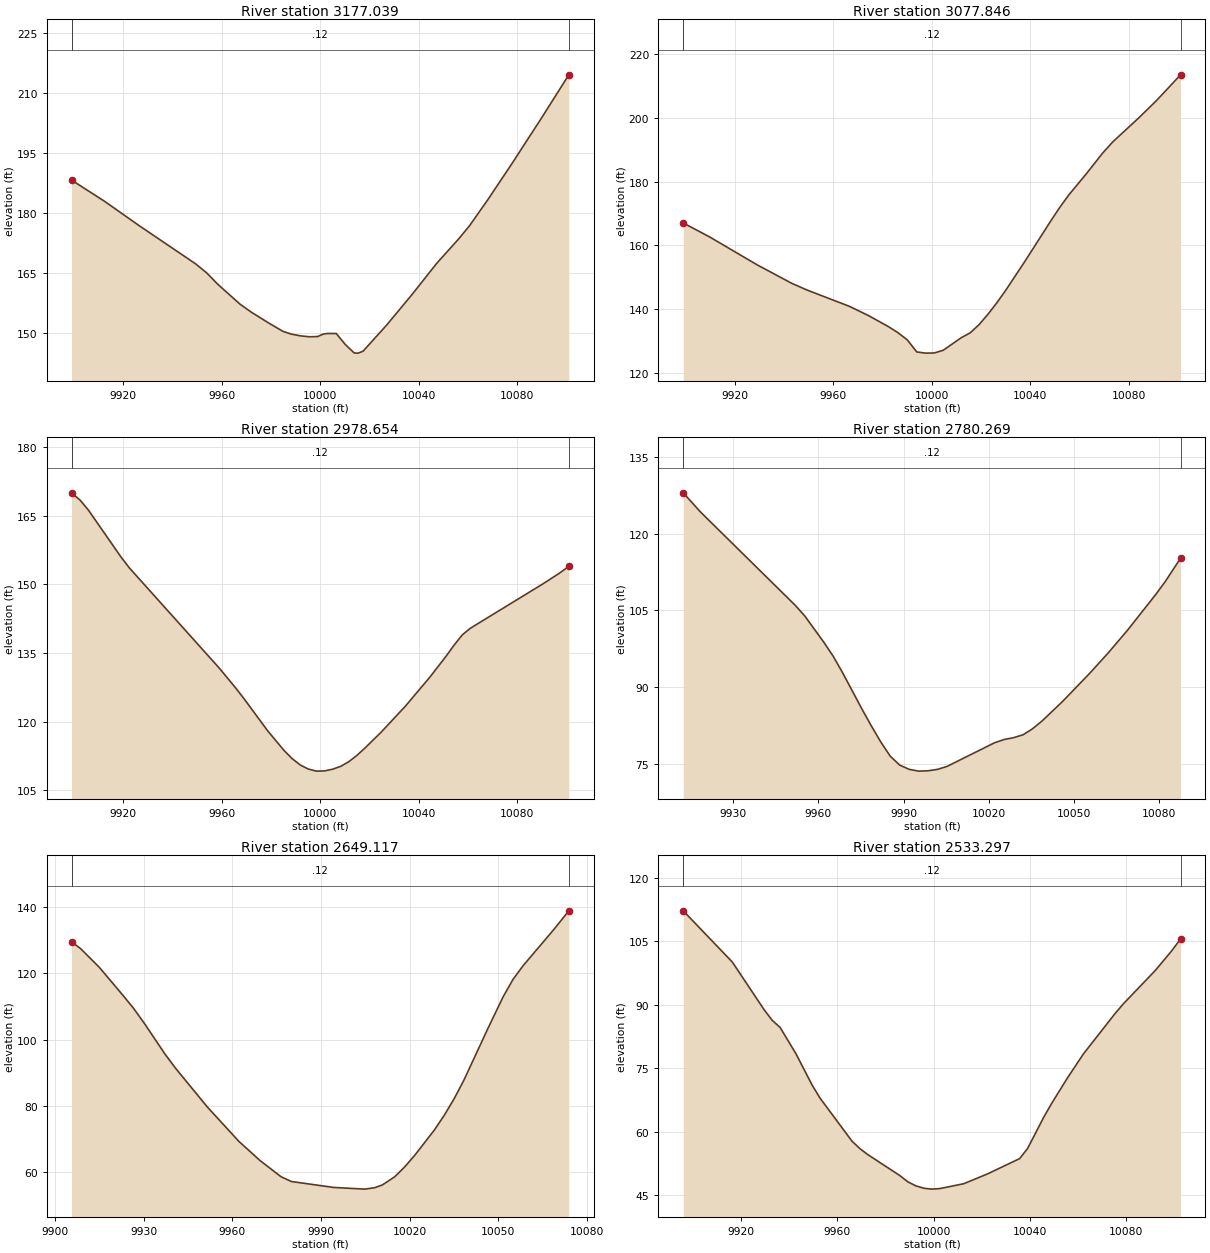
Type RM Length L Ch R = 1 ,3177.039,99.192600,99.192600,99.192600
XS GIS Cut Line= 6
1235041.63585524 839251.447651581234979.26726232 839310.31448853
1234964.63587224839339.8858775461234948.75884434839359.738395559
1234930.81936158839376.5916200911234904.54554099 839396.47894363
#Sta/Elev= 30
9899.125188.30349912.609182.96039926.897176.76189949.454167.35649953.966165.0776
9958.477162.2269  9967.5157.25239972.011155.27889979.526152.39039984.887150.4659
9988.166149.7811  9991.9149.33349995.633149.0954    9999149.1536   10001  149.71
 10002.9149.922810006.53149.909310010.16147.200610013.79145.0438 10015.5145.0035
10017.42145.495710026.77151.879510037.27159.660310047.23167.429210056.14173.5414
10060.65176.917810067.94183.324410077.73192.344110090.08204.097210100.89214.6419
#Mann= 3 , 0 , 0
9899.125    0.12       09899.125    0.12       010100.89    0.12       0
#XS Ineff= 2 , 0
       0                               0
Bank Sta=9899.125,10100.89
Exp/Cntr=0.3,0.1

Type RM Length L Ch R = 1 ,3077.846,99.192500,99.192500,99.192500
XS GIS Cut Line= 6
1235004.58934948839203.7757922491234964.00171074839225.531911042
1234923.81207641839251.5790510651234916.44418125839254.746397297
 1234867.8414841839278.1258978241234825.36704505839295.902073921
#Sta/Elev= 30
9899.035167.01119909.698162.64069929.255153.77439943.144148.03849949.431 145.918
9966.562140.82169974.382 137.8839982.201134.5384 9986.11132.6344 9990.02130.3103
9993.852126.52219997.441126.148510000.99126.196110004.63127.059110011.91130.9887
10015.55132.509310019.19135.116710022.84138.416710026.48142.054810030.12146.0282
10037.45154.574510048.32167.695910051.96171.927910055.59175.7921 10062.7182.4292
10069.29188.891810073.37192.399510084.04 200.01510091.15205.378610100.98213.5112
#Mann= 3 , 0 , 0
9899.035    0.12       09899.035    0.12       010100.98    0.12       0
#XS Ineff= 2 , 0
       0                               0
Bank Sta=9899.035,10100.98
Exp/Cntr=0.3,0.1

Type RM Length L Ch R = 1 ,2978.654,198.385100,198.385100,198.385100
XS GIS Cut Line= 5
1235005.22280325839145.6989184931234946.51919444839155.001700511
1234906.12102331 839158.21648411 1234904.1279318839158.382575128
1234804.35452144839164.946144946
#Sta/Elev= 30
9899.038 170.013 9902.55168.39929905.872166.25959919.159155.95429922.481153.6217
9959.015131.69089965.598127.40119968.889 125.1299978.763117.91749985.345113.6651
9988.636  111.889991.927110.49359995.219109.5954 9998.51109.1477 10001.8109.1947
10005.09109.569910008.38110.204510011.66111.215210014.95112.602110018.24114.2166
10024.82117.691610034.68123.394110044.54129.685110051.12134.262110054.41136.7122
 10057.7138.932110060.98140.388910090.57150.137510097.15152.429110100.99153.9296
#Mann= 3 , 0 , 0
9899.038    0.12       09899.038    0.12       010100.99    0.12       0
#XS Ineff= 2 , 0
       0                               0
Bank Sta=9899.038,10100.99
Exp/Cntr=0.3,0.1

Type RM Length L Ch R = 1 ,2780.269,131.152200,131.152200,131.152200
XS GIS Cut Line= 2
1234991.24613366838978.1519806711234819.37113366838944.297814004
#Sta/Elev= 30
9912.408128.01599918.418124.29959951.857105.9928  9955.2103.92169961.88898.79329
9965.23296.020829968.57692.760619975.26485.775069978.60882.435789981.95179.27083
9985.29576.473399988.63974.713259991.983 73.87359995.327 73.52469998.67173.58962
10002.0173.8717910005.3674.4537910022.0879.0807410025.4279.7133510028.77 80.0764
10032.1180.6419310035.4581.81788 10038.883.3418610046.1587.2333410055.5292.63949
 10062.296.7243710068.89101.101610078.92108.161810082.27110.695410087.59115.2057
#Mann= 3 , 0 , 0
9912.408    0.12       09912.408    0.12       010087.59    0.12       0
#XS Ineff= 2 , 0
       0                               0
Bank Sta=9912.408,10087.59
Exp/Cntr=0.3,0.1

Type RM Length L Ch R = 1 ,2649.117,115.819100,115.819100,115.819100
XS GIS Cut Line= 6
1235040.72530033 838880.495730671234952.33170683838842.993297178
1234933.75277123838838.2923140611234917.74970354838835.764491101
1234902.34882237838833.1554449571234881.95225568838827.352912649
#Sta/Elev= 30
9905.635129.56399908.766127.4402 9914.98121.9093 9923.38 113.0169926.586109.5036
9930.149105.08079937.27795.627669940.84191.359219951.53379.723279962.22569.31416
9969.35263.54457 9976.4858.630759980.04457.16736  9994.355.3907310004.8254.87586
10008.2155.3110910010.7756.1350110014.9858.6184310018.3661.6111310021.7365.09335
10028.3772.72502 10031.777.1479810035.0282.1167910038.3487.7386410046.42103.2737
10051.65112.993310055.03118.275610058.45 122.41910068.68133.160210073.85138.9059
#Mann= 3 , 0 , 0
9905.635    0.12       09905.635    0.12       010073.85    0.12       0
#XS Ineff= 2 , 0
       0                               0
Bank Sta=9905.635,10073.85
Exp/Cntr=0.3,0.1

Type RM Length L Ch R = 1 ,2533.297,0.000000,0.000000,0.000000
XS GIS Cut Line= 2
1235120.34914292838763.6713672441234915.90596757838733.779558084
#Sta/Elev= 30
9895.988112.23079916.373100.12379929.63688.809389932.95286.339029936.26784.62102
9942.89978.34506 9949.5371.022779952.78167.971349966.10957.747199969.42455.97481
 9972.7454.555869986.00349.612529989.31948.131819992.63447.18909 9995.9546.62588
9999.26646.4148910002.5846.5410610012.5347.6951710022.4850.0321210035.74 53.6275
10039.0556.0206510045.6963.33691   1004966.6302110055.6372.7224810062.2678.39334
10075.5388.0308810078.8490.2311710092.1198.1240410098.74102.638310102.61105.5712
#Mann= 3 , 0 , 0
9895.988    0.12       09895.988    0.12       010102.61    0.12       0
#XS Ineff= 2 , 0
       0                               0
Bank Sta=9895.988,10102.61
Exp/Cntr=0.3,0.1